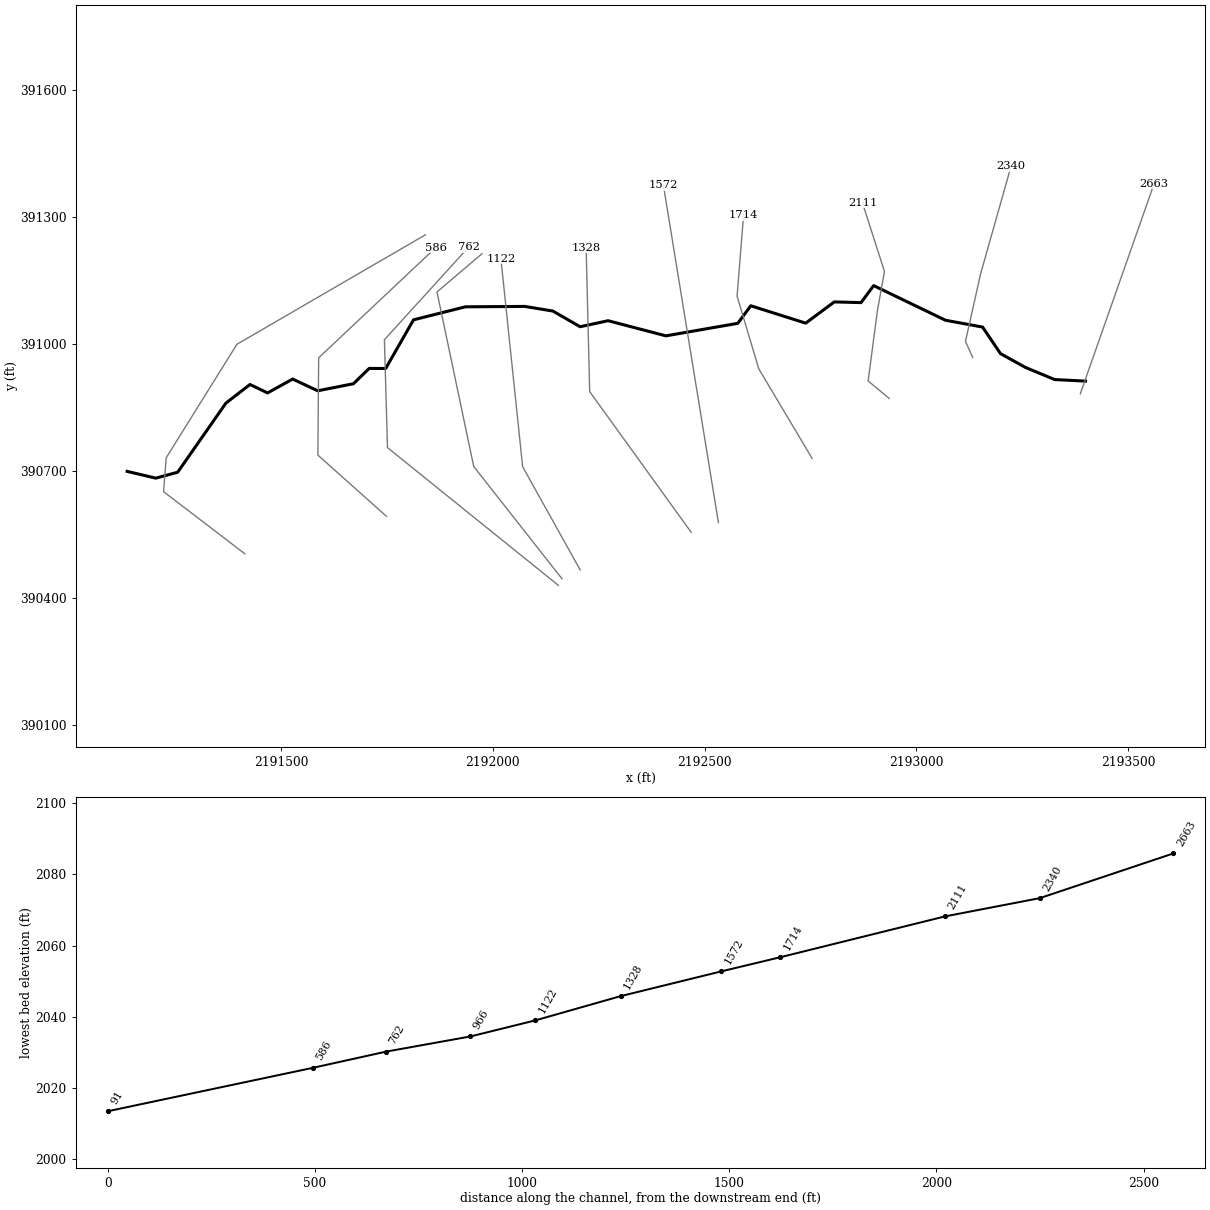
--- NIGAPRN.prj (project) ---

Proj Title=NIGAPRN
Current Plan=p01
Default Exp/Contr=0,0
English Units
Geom File=g01
Flow File=f01
Plan File=p01
Background Map Layer=Inundation Boundary (01pct Value_0)
BEGIN DESCRIPTION:
----------MODEL BY WOOD PLC 2021----------
Stream Name: Nigh Gap Run
Flood Zone: Enhanced Approximate
Pocahontas County, WV
HEC-RAS Version: RAS 6.1
Vertical Datum: NAVD88
Projection: NAD 1983 StatePlane West Virginia S FIPS 4702 (US Feet)
Terrain: 1-meter LIDAR (FEMA Region III 3DEP collected 2016-2018)
Land Use: 2019 NLCD
Hydrologic Method:
WV SIR2010-5033 regression equations
Model Notes:
Normal depth tie in to Oldham Run
END DESCRIPTION:
DSS Export Rating Curves= 0
DSS Export Rating Curve Sorted= 0
DSS Export Volume Flow Curves= 0
DXF OffsetX= 0
DXF OffsetY= 0
DXF ScaleX= 0
DXF ScaleY= 0

--- NIGAPRN.p01 (plan) ---

Plan Title=Floodplain
Program Version=6.00
Short Identifier=Floodplain
Geom File=g01
Flow File=f01
Subcritical Flow
K Sum by GR= 0
Std Step Tol= 0.01
Critical Tol= 0.01
Num of Std Step Trials= 20
Max Error Tol= 0.3
Flow Tol Ratio= 0.001
Split Flow NTrial= 30
Split Flow Tol= 0.02
Split Flow Ratio= 0.02
Log Output Level= 0
Friction Slope Method= 1
Unsteady Friction Slope Method= 2
Unsteady Bridges Friction Slope Method= 1
Parabolic Critical Depth
Global Vel Dist= 0 , 0 , 0
Global Log Level= 0
CheckData=False
Encroach Param=-1 ,0,0, 0
Mapping Interval=1HOUR
Computation Time Step Use Courant=        0
Computation Time Step Use Time Series=    0
Computation Time Step Count To Double=0
Computation Time Step Max Doubling=0
Computation Time Step Max Halving=0
Computation Time Step Residence Courant=0
Run HTab= 0
Run UNet= 0
Run Sediment= 0
Run PostProcess= 0
Run WQNet= 0
Run RASMapper=-1
UNET Theta= 0
UNET Theta Warmup= 0
UNET ZTol= 0
UNET ZSATol= 0
UNET MxIter= 0
UNET Max Iter WO Improvement= 0
UNET MaxInSteps= 0
UNET DtIC= 0
UNET DtMin= 0
UNET MaxCRTS= 0
UNET WFStab= 0
UNET SFStab= 0
UNET WFX= 1
UNET SFX= 1
UNET Gravity=32.174
UNET 1D Methodology=Finite Difference
UNET DSS MLevel= 1
UNET Pardiso=0
UNET DZMax Abort= 0
UNET Use Existing IB Tables= 0
UNET Froude Reduction=False
UNET Froude Limit= 0
UNET Froude Power= 0
UNET D1 Cores= 0
UNET WindReference=Eulerian
UNET WindDragFormulation=Hsu (1988)
UNET D2 Coriolis=0
UNET D2 Cores= 0
UNET D2 Theta= 1
UNET D2 Theta Warmup= 1
UNET D2 Z Tol= 0.01
UNET D2 Volume Tol= 0.01
UNET D2 Max Iterations= 20
UNET D2 Equation= 0
UNET D2 RampUpFraction=0.1
UNET D2 TimeSlices= 1
UNET D2 Turbulence Formulation=Non-Conservative (original)
UNET D2 Eddy Viscosity=0.3
UNET D2 Transverse Eddy Viscosity=0.1
UNET D2 Smagorinsky Mixing=0
UNET D2 BCVolumeCheck=0
UNET D2 Cores=0
UNET D2 SolverType=PARDISO (Direct)
UNET D2 Minimum Iterations= 2147483647
UNET D2 Maximum Iterations= 2147483647
UNET D2 Restart Number= 10
UNET D2 Relaxation Coeff=1.3
UNET D2 SOR Precondition Iterations= 10
UNET D2 ILUT Maximum Fill= 8
UNET D2 ILUT Tolerance=1E-08
UNET D1D2 MaxIter= 0
UNET D1D2 ZTol=0.01
UNET D1D2 QTol=0.1
UNET D1D2 MinQTol=1
Write IC File= 0
Write IC File at Fixed DateTime=0
Write IC File at Sim End=0
Echo Input=False
Echo Parameters=False
Echo Output=False
Write Detailed= 0
HDF Write Warmup=0
HDF Write Time Slices=0
HDF Flush=0
HDF Compression= 1
HDF Chunk Size= 1
HDF Spatial Parts= 1
HDF Use Max Rows=0
HDF Fixed Rows= 1
Calibration Method= 0
Calibration Iterations= 20
Calibration Max Change=0.05
Calibration Tolerance=0.2
Calibration Maximum=1.5
Calibration Minimum=0.5
Calibration Optimization Method= 1
WQ AD Non Conservative
WQ ULTIMATE=-1
WQ Max Comp Step=1HOUR
WQ Output Interval=15MIN
WQ Output Selected Increments= 0
WQ Output face flow=0
WQ Output face velocity=0
WQ Output face area=0
WQ Output face dispersion=0
WQ Output cell volume=0
WQ Output cell surface area=0
WQ Output cell continuity=0
WQ Output cumulative cell continuity=0
WQ Output face conc=0
WQ Output face dconc_dx=0
WQ Output face courant=0
WQ Output face peclet=0
WQ Output face adv mass=0
WQ Output face disp mass=0
WQ Output cell mass=0
WQ Output cell source sink temp=0
WQ Output nsm pathways=0
WQ Output nsm derived pathways=0
WQ Create Restart=0
WQ Fixed Restart=0
WQ System Summary=0
WQ Write To DSS=0
Sorting and Armoring Iterations= 10
XS Update Threshold= 0.02
Bed Roughness Predictor= 0
Hydraulics Update Threshold= 0.02
Energy Slope Method= 1
Volume Change Method= 1
Sediment Retention Method= 0
Sediment TS Multiplier= 1
Warm Up Method= 0
XS Weighting Method= 0
Number of US Weighted Cross Sections= 1
Number of DS Weighted Cross Sections= 1
Upstream XS Weight=0
Main XS Weight=1
Downstream XS Weight=0
Number of DS XS's Weighted with US Boundary= 1
Upstream Boundary Weight= 1
Weight of XSs Associated with US Boundary= 0
Number of US XS's Weighted with DS Boundary= 1
Downstream Boundary Weight= 0.5
Weight of XSs Associated with DS Boundary= 0.5
Percentile Method= 0
Sediment Output Level= 3
Mass or Volume Output= 0
Output Increment Type= 1
Profile and TS Output Increment= 1
Transport Output Increment 1
XS Output Flag= 0
XS Output Increment= 10
Read HDF5 Sediment Hotstart= 0
Sediment Hotstart Type= 0
Write Gradation File= 0
Read Gradation Hotstart= 0
Write HDF5 File= 1
Write Binary Output= 1
Write DSS Sediment File= 0
DSS Sediment Output Type= 1
SV Curve= 0
Specific Gage Flag= 0
Subcell Erosion Methods= 0
Subcell Deposition Methods= 0
Advection Scheme= 1
Matrix Solver= 0
Implicit Weighting Factor= 1
Maximum Outer Loop Convergence Iterations= 5
Convergence Maximum Absolute= 0.001
Convergence RMSE= 0.0001
Grain Fractions Max Abs Error= 0.001
Max Subgrid Regions= 1
Max Subgrid Length Scale= 3.402823E+38
Initial Layer Thickness= 3.402823E+38
Min Layer Thickness= 3.402823E+38
Max Layer Thickness= 3.402823E+38
Number of Layers= 5

--- NIGAPRN.f01 (steady flow) ---

Flow Title=Flow
Program Version=6.00
Number of Profiles= 6
Profile Names=01pct,10pct,04pct,02pct,0_2pct,01plus
River Rch & RM=NIGAPRN,Main            ,2663
     525     276     368     444     734     776
Boundary for River Rch & Prof#=NIGAPRN,Main            , 1
Up Type= 0
Dn Type= 3
Dn Slope=0.02276
Boundary for River Rch & Prof#=NIGAPRN,Main            , 2
Up Type= 0
Dn Type= 3
Dn Slope=0.02276
Boundary for River Rch & Prof#=NIGAPRN,Main            , 3
Up Type= 0
Dn Type= 3
Dn Slope=0.02276
Boundary for River Rch & Prof#=NIGAPRN,Main            , 4
Up Type= 0
Dn Type= 3
Dn Slope=0.02276
Boundary for River Rch & Prof#=NIGAPRN,Main            , 5
Up Type= 0
Dn Type= 3
Dn Slope=0.02276
Boundary for River Rch & Prof#=NIGAPRN,Main            , 6
Up Type= 0
Dn Type= 3
Dn Slope=0.02276
DSS Import GetInterval= 0
DSS Import GetPeak= 0
DSS Import FillOption= 0

--- NIGAPRN.g01 (geometry) ---

Geom Title=Geometry
Program Version=6.10

River Reach=NIGAPRN         ,Main
Reach XY= 30
2193399.33021006390912.7325872062193326.50559052390916.383088925
2193257.35540873390945.1069977982193198.60626473390977.624974185
     2193156.315      391040.308 2193068.6473796391056.451747422
     2192899.034       391138.25     2192869.324      391098.077
2192806.12921349391099.722921417     2192738.595       391049.61
     2192608.888      391090.632      2192578.29      391049.191
      2192408.48      391019.599     2192271.952      391055.336
     2192205.869      391041.093     2192141.703      391078.138
     2192075.086      391089.101     2191934.979      391088.162
     2191812.518      391057.427     2191746.805      390942.512
     2191707.877      390942.685     2191670.679      390906.547
     2191586.251      390889.885     2191527.209      390917.613
      2191467.96      390884.817     2191426.421      390904.784
     2191369.525      390860.724     2191255.639      390697.591
     2191203.927      390683.615     2191136.305      390699.596

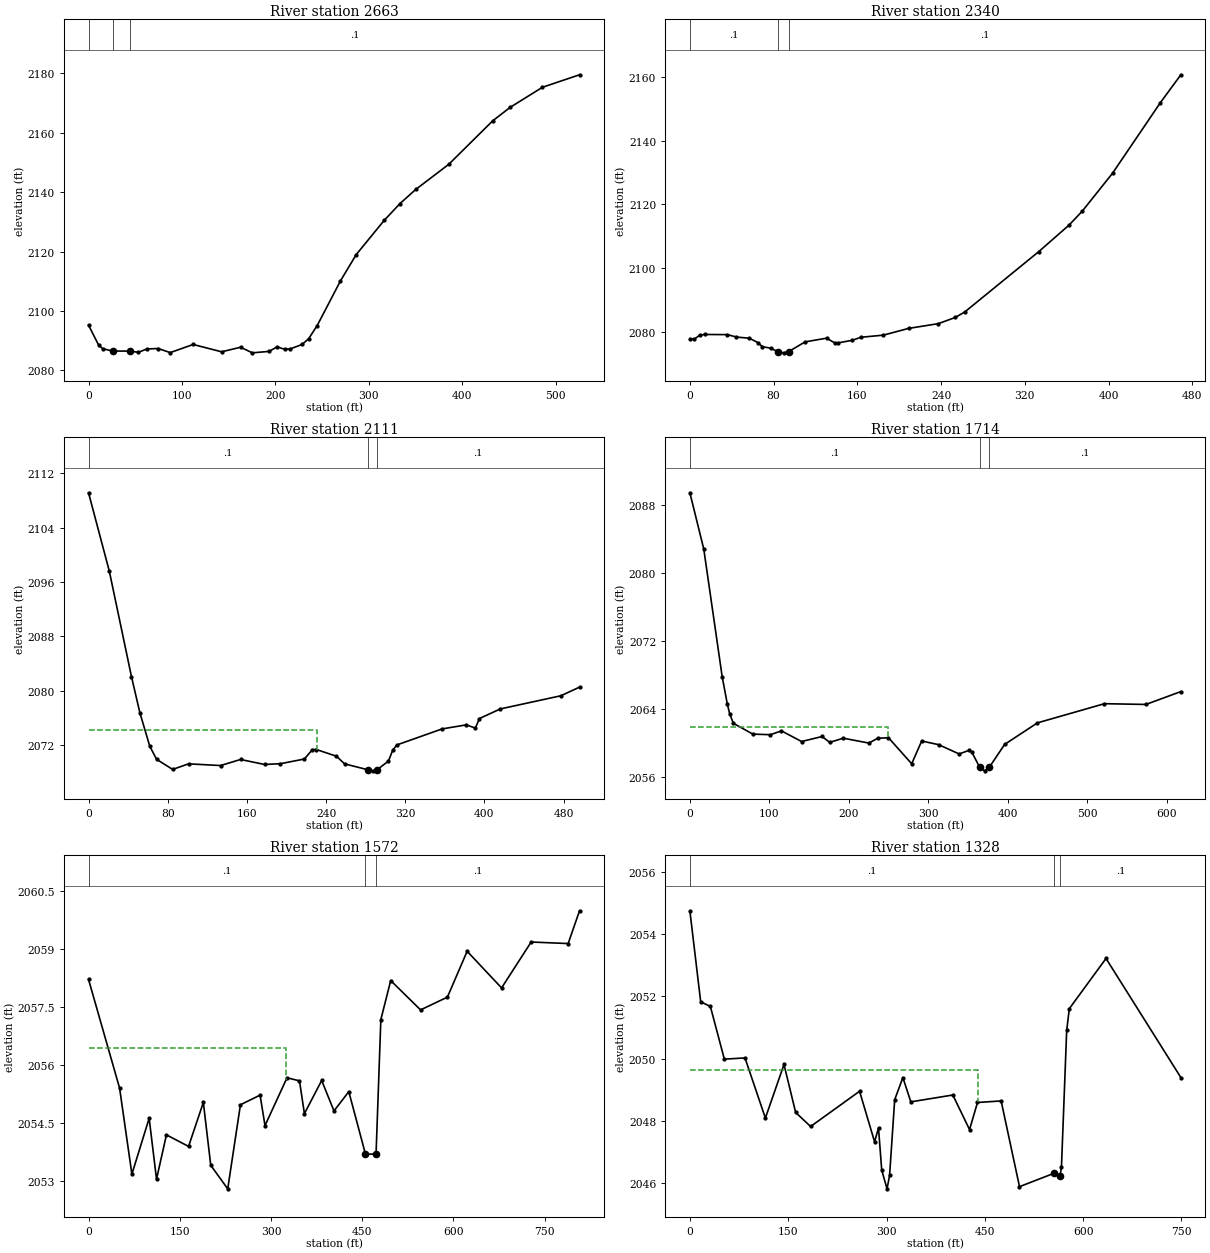
Type RM Length L Ch R = 1 ,2663    ,322.7,322.7,322.7
XS GIS Cut Line= 2
2193387.05158743390882.7543384442193561.23066312 391378.63662736
#Sta/Elev= 30
       0 2095.22      11 2088.38    15.3 2087.28   25.84 2086.4844.347642086.487
    53.4 2086.06    62.4  2087.2    74.6 2087.34    87.4 2085.97     112  2088.7
   142.5 2086.24   162.8 2087.78   175.3 2085.89   193.4 2086.38   201.8 2087.91
   210.3 2087.05   216.1 2087.24   228.7 2088.72   235.7 2090.68   244.8 2095.09
   269.7 2110.13   286.6    2119   316.5 2130.51   333.3 2136.13   350.2 2140.91
   385.6 2149.38   432.6 2164.02   451.4 2168.59   485.9 2175.34   525.6 2179.55
#Mann= 3 ,0,0
       0      .1       0   25.84    .045       044.34764      .1       0
Bank Sta=25.84,44.34764
XS Rating Curve= 0 ,0
Exp/Cntr=0.3,0.1

Type RM Length L Ch R = 1 ,2340    ,229,229,229
XS GIS Cut Line= 4
2193133.03811062390968.4211194212193115.88305227391006.630113016
2193151.75271973391166.4840658082193223.49205464391419.911064138
#Sta/Elev= 30
       0 2077.68     4.3 2077.68     9.6 2078.87      14  2079.1    35.9 2079.05
    44.5 2078.29    56.8 2077.92      65 2076.55    69.1 2075.29    77.3 2074.78
   83.74 2073.74    89.6 2073.33    94.5 2073.74   110.1 2076.77   130.6 2077.94
   138.8 2076.38   141.4 2076.45   155.2 2077.27   163.4 2078.22   184.9 2078.89
     209 2081.01   237.4  2082.5   253.6 2084.45   262.6 2086.16   333.2 2105.09
   362.3 2113.47   374.8  2117.8   403.9 2129.79   449.6 2151.96   469.1 2160.68
#Mann= 3 ,0,0
       0      .1       0   83.74    .045       0    94.5      .1       0
Bank Sta=83.74,94.5
XS Rating Curve= 0 ,0
Exp/Cntr(USF)=0,0
Exp/Cntr=0.3,0.1

Type RM Length L Ch R = 1 ,2111    ,397.1,397.1,397.1
XS GIS Cut Line= 5
2192935.88887321 390871.804435242192886.07391413390913.040766947
2192907.97684045391079.3662198852192924.61214913391171.490353397
 2192872.7208471391333.480469159
#Sta/Elev= 30
       0 2109.13      21 2097.59    43.4 2082.06    51.9 2076.74    61.9 2071.81
    68.8 2069.89      85 2068.41   101.1 2069.23   133.4 2068.98   153.6 2069.87
   177.8 2069.14   193.9 2069.25   218.1 2069.94   226.2 2071.33   230.2 2071.34
   250.5 2070.35   258.7 2069.23282.34082068.353   287.1  2068.2291.14082068.318
     303 2069.63   307.4 2071.25   311.5 2072.01   357.2 2074.37   381.8 2074.97
   390.8 2074.49     395  2075.9     416 2077.31   477.2 2079.25   496.1 2080.52
#Mann= 3 ,0,0
       0      .1       0282.3408    .045       0291.1408      .1       0
#XS Ineff= 2 , 0
          230.42 2074.19
Permanent Ineff=
       F       F
Bank Sta=282.3408,291.1408
XS Rating Curve= 0 ,0
Exp/Cntr(USF)=0,0
Exp/Cntr=0.3,0.1

Type RM Length L Ch R = 1 ,1714    ,142,142,142
XS GIS Cut Line= 4
2192753.80251507 390730.17481459 2192627.9052274390941.588942951
2192576.57986971391113.5288912182192591.94270448391305.033966644
#Sta/Elev= 30
       0 2089.38    17.5 2082.77    40.7 2067.76    47.1 2064.59    50.1 2063.44
    54.7 2062.33    79.2 2061.06   101.3 2060.99   115.2 2061.44   140.5 2060.19
   166.4 2060.78   175.8 2060.09     193 2060.58   225.1 2060.01   236.3 2060.57
   249.8 2060.64     279 2057.58   291.6 2060.25     313 2059.82   338.7 2058.73
   351.6 2059.17   354.8 2058.93   364.5 2057.17   370.8 2056.75   376.8 2057.19
   395.9 2059.85   437.2 2062.38   521.5 2064.63   573.6 2064.54   617.6 2066.05
#Mann= 3 ,-1,0
       0      .1       0   364.5    .045       0   376.8      .1       0
#XS Ineff= 2 , 0
          248.85 2061.95
Permanent Ineff=
       F       F
Bank Sta=364.5,376.8
XS Rating Curve= 0 ,0
Exp/Cntr(USF)=0,0
Exp/Cntr=0.3,0.1

Type RM Length L Ch R = 1 ,1572    ,243.5,243.5,243.5
XS GIS Cut Line= 2
2192532.52227463390578.7948486712192402.53625322391375.696040731
#Sta/Elev= 30
       0 2058.22    51.1  2055.4    71.3 2053.17    99.7 2054.62   111.8 2053.04
   128.1 2054.19   164.5 2053.89   188.8 2055.03     201  2053.4   228.9 2052.79
   249.8 2054.97   282.1 2055.22   290.2 2054.43   326.4 2055.67   346.9 2055.59
     355 2054.74   383.4  2055.6   403.6 2054.81     428 2055.31   455.4 2053.69
   472.8 2053.69   480.7 2057.18   496.9 2058.19     546 2057.43   590.1 2057.76
   622.6 2058.95   679.2    2058   727.9 2059.19   788.7 2059.15   807.4    2060
#Mann= 3 ,0,0
       0      .1       0   455.4    .045       0   472.8      .1       0
#XS Ineff= 2 , 0
          324.51 2056.45
Permanent Ineff=
       F       F
Bank Sta=455.4,472.8
XS Rating Curve= 0 ,0
Exp/Cntr(USF)=0,0
Exp/Cntr=0.3,0.1

Type RM Length L Ch R = 1 ,1328    ,206.1,206.1,206.1
XS GIS Cut Line= 3
2192468.15953259390555.7718292072192228.49969522390887.985107402
2192220.19098026391227.314716232
#Sta/Elev= 30
       0 2054.74    16.5 2051.82    31.3 2051.67    52.6 2049.98    84.1 2050.02
   115.2 2048.09   143.6 2049.81   161.4 2048.27   184.2 2047.82   258.9 2048.95
   281.8 2047.33   287.8 2047.77   292.7 2046.42   300.8 2045.82   304.7 2046.25
   312.5 2048.68     325 2049.39   337.1 2048.61   401.2 2048.83   426.7 2047.72
   438.8 2048.59   474.9 2048.64   502.9 2045.89555.22372046.316564.7153 2046.23
   566.9 2046.51   574.9  2050.9   578.9  2051.6   634.9 2053.21   749.1 2049.39
#Mann= 3 ,0,0
       0      .1       0555.2237    .045       0564.7153      .1       0
#XS Ineff= 2 , 0
          439.44 2049.63
Permanent Ineff=
       F       F
Bank Sta=555.2237,564.7153
XS Rating Curve= 0 ,0
Exp/Cntr=0.3,0.1

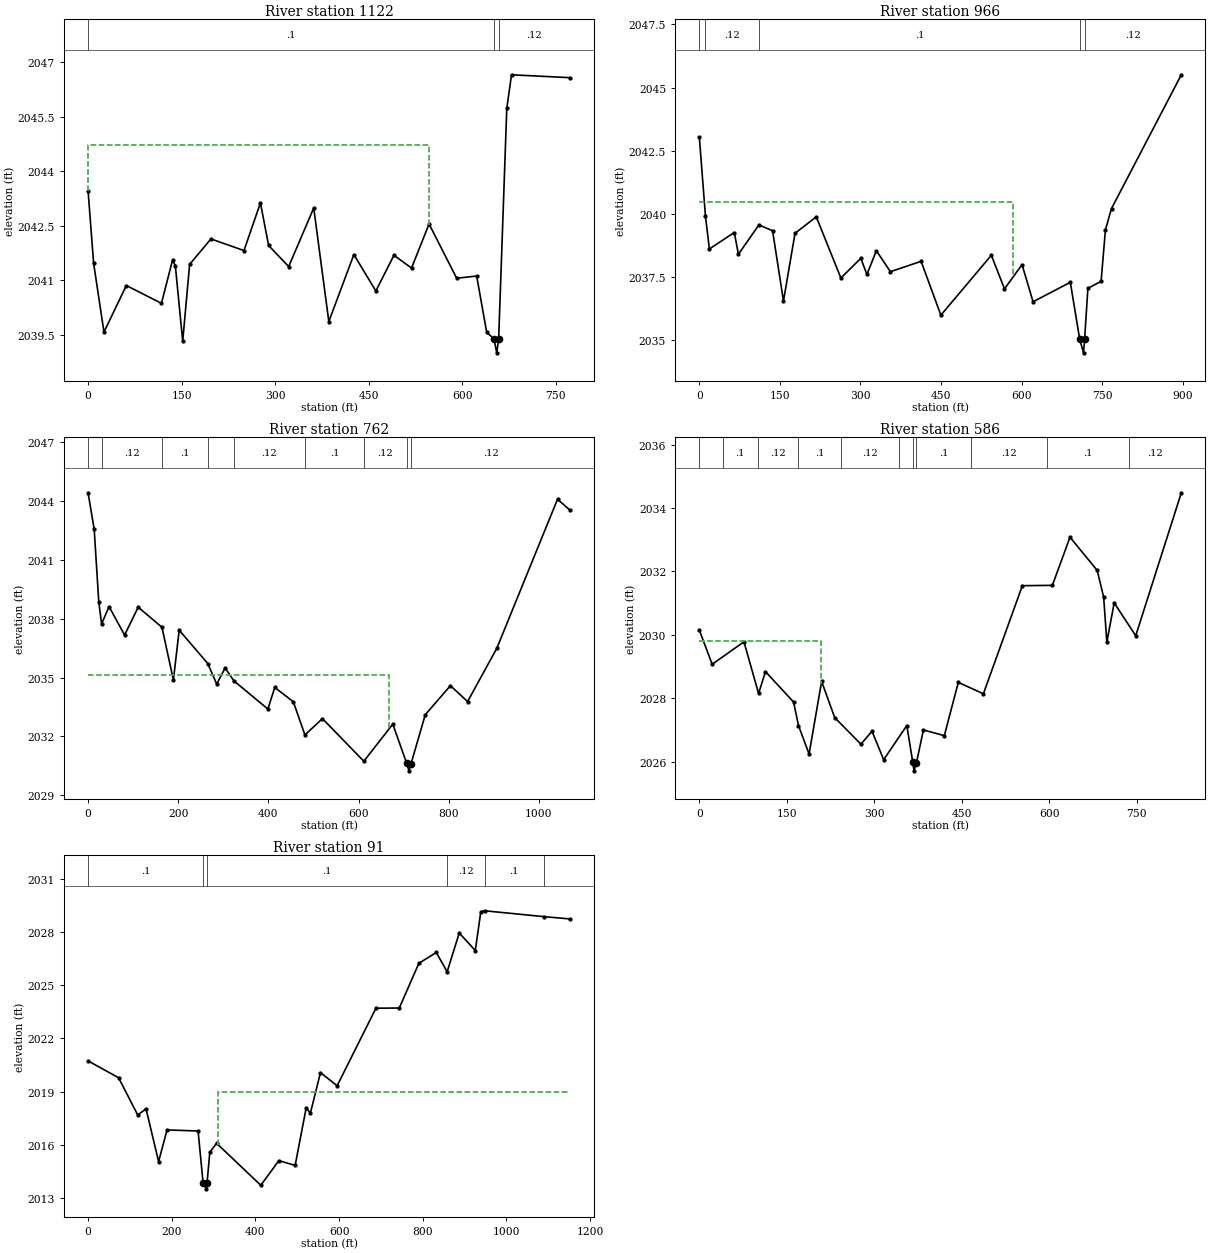
Type RM Length L Ch R = 1 ,1122    ,156.4,156.4,156.4
XS GIS Cut Line= 3
2192206.05686001390466.9039177622192070.22965135390710.615167566
2192018.85719189391202.106067826
#Sta/Elev= 30
       0 2043.46     8.9 2041.47    25.5 2039.58    61.4 2040.86   117.7 2040.37
   135.5 2041.56     140  2041.4   151.8 2039.33   162.9 2041.44   197.1 2042.14
   250.1 2041.82   276.5 2043.13   289.6 2041.96   321.8 2041.38     362 2042.99
   386.2 2039.87   426.4 2041.71   461.6 2040.71   490.7 2041.69   518.9 2041.34
     547 2042.55   591.3 2041.06   623.4 2041.12   639.5 2039.57     651  2039.4
   655.6 2039.01658.66052039.392   671.7 2045.73   679.3 2046.65   773.2 2046.57
#Mann= 3 ,0,0
       0      .1       0     651    .045       0658.6605     .12       0
#XS Ineff= 2 , 0
          546.18 2044.73
Permanent Ineff=
       F       F
Bank Sta=651,658.6605
XS Rating Curve= 0 ,0
Exp/Cntr(USF)=0,0
Exp/Cntr=0.3,0.1

Type RM Length L Ch R = 1 ,966     ,203.5,203.5,203.5
XS GIS Cut Line= 4
 2192163.2091304390445.9796831632191954.68135621390711.156385295
2191867.97584787391123.2175556752191973.98804323391213.407561405
#Sta/Elev= 30
       0 2043.04    11.4 2039.91    18.7 2038.62    65.1 2039.27    72.8 2038.41
   110.9 2039.57   136.4 2039.34   156.7 2036.56   178.2 2039.24   217.8 2039.89
   263.6 2037.47   300.7 2038.25   312.1 2037.61   329.7 2038.55   355.8 2037.72
     413 2038.13   449.8    2036   543.8 2038.37   568.3 2037.04     601    2038
   621.5 2036.53   690.9  2037.3  708.43 2035.04   715.5 2034.51717.4697 2035.04
   723.6 2037.06   748.2 2037.34   756.3 2039.38   767.6 2040.22   897.6 2045.51
#Mann= 5 ,-1,0
       0      .1       0    11.4     .12       0   110.9      .1       0
  708.43    .045       0717.4697     .12       0
#XS Ineff= 2 , 0
          584.72 2040.47
Permanent Ineff=
       F       F
Bank Sta=708.43,717.4697
XS Rating Curve= 0 ,0
Exp/Cntr(USF)=0,0
Exp/Cntr=0.3,0.1

Type RM Length L Ch R = 1 ,762     ,176.4,176.4,176.4
XS GIS Cut Line= 4
2192154.72832574390430.3737801512191751.06170036390755.660538927
2191743.79905157391010.4172435022191942.85759163391229.355641279
#Sta/Elev= 30
       0 2044.42    13.6 2042.55    23.7 2038.87      30 2037.74    46.5 2038.62
      81 2037.17   111.2 2038.59   163.8 2037.57   189.3 2034.88   202.1 2037.42
   265.5 2035.72   285.4 2034.67   304.1  2035.5   323.2 2034.84   398.8  2033.4
   414.2  2034.5   455.3 2033.77     481 2032.08   519.9 2032.91   611.7 2030.74
     676 2032.63706.62412030.645     712 2030.25 716.0242030.583     748 2033.11
   803.8 2034.59   841.9 2033.78   906.8  2036.5  1041.4 2044.09  1069.2 2043.53
#Mann= 9 ,-1,0
       0      .1       0      30     .12       0   163.8      .1       0
   265.5     .12       0   323.2     .12       0     481      .1       0
   611.7     .12       0706.6241    .045       0 716.024     .12       0
#XS Ineff= 2 , 0
          667.77 2035.11
Permanent Ineff=
       F       F
Bank Sta=706.6241,716.024
XS Rating Curve= 0 ,0
Exp/Cntr=0.3,0.1

Type RM Length L Ch R = 1 ,586     ,495.3,495.3,495.3
XS GIS Cut Line= 4
2191748.59266193390593.5417597292191586.71820142390738.027725138
2191588.57193705390967.7364338622191865.14739312391228.037063302
#Sta/Elev= 30
       0 2030.15      22 2029.07    76.5 2029.78   101.6 2028.15   113.4 2028.84
   161.6 2027.88     170 2027.14   188.2 2026.24   209.7 2028.53   232.1 2027.39
   277.1 2026.55   296.1 2026.96   316.1 2026.06   355.8 2027.14365.9944 2025.98
   368.1 2025.71   372.3 2025.96   384.2    2027   420.1 2026.82   444.1  2028.5
   487.1 2028.14   553.9 2031.55   605.4 2031.56   635.6 2033.08   682.3 2032.03
   693.3 2031.19   698.8 2029.77   711.4 2031.01   748.3 2029.97   826.5 2034.48
#Mann= 11 ,-1,0
       0     .12       0      40      .1       0     100     .12       0
     170      .1       0  242.11     .12       0  342.11      .1       0
365.9944    .045       0   372.3      .1       0  466.51     .12       0
  596.51      .1       0  736.51     .12       0
#XS Ineff= 2 , 0
          209.01  2029.8
Permanent Ineff=
       F       F
Bank Sta=365.9944,372.3
XS Rating Curve= 0 ,0
Exp/Cntr(USF)=0,0
Exp/Cntr=0.3,0.1

Type RM Length L Ch R = 1 ,91      ,,,
XS GIS Cut Line= 5
2191414.15221771390505.0850721212191222.40483019390651.616727052
2191228.54325862390731.7272585082191395.47355189390999.652295745
2191840.71087196391258.221157143
#Sta/Elev= 30
       0 2020.73      73 2019.78   118.7 2017.68   138.5 2018.03   168.6 2015.06
   188.8 2016.84     263 2016.78     275 2013.84     283 2013.52  284.41 2013.86
     291 2015.58   307.1 2016.09   412.9 2013.72     456 2015.11     495 2014.84
   521.3 2018.07   531.5 2017.79   555.5 2020.07   595.4 2019.33   688.2  2023.7
   743.9 2023.71   790.8 2026.23   832.4 2026.84   858.4 2025.75   887.3 2027.94
   925.7 2026.95   938.8 2029.13   948.1 2029.19  1089.6 2028.86  1152.2 2028.73
#Mann= 6 ,-1,0
       0      .1       0     275    .045       0  284.41      .1       0
   858.4     .12       0   948.1      .1       0  1089.6     .12       0
#XS Ineff= 2 , 0
       0                  310.99       0    2019
Permanent Ineff=
       F       F
Bank Sta=275,284.41
XS Rating Curve= 0 ,0
Exp/Cntr(USF)=0,0
Exp/Cntr=0.3,0.1
LCMann Table=0

Chan Stop Cuts=-1
Use User Specified Reach Order=0
Composite Channel Slope=5